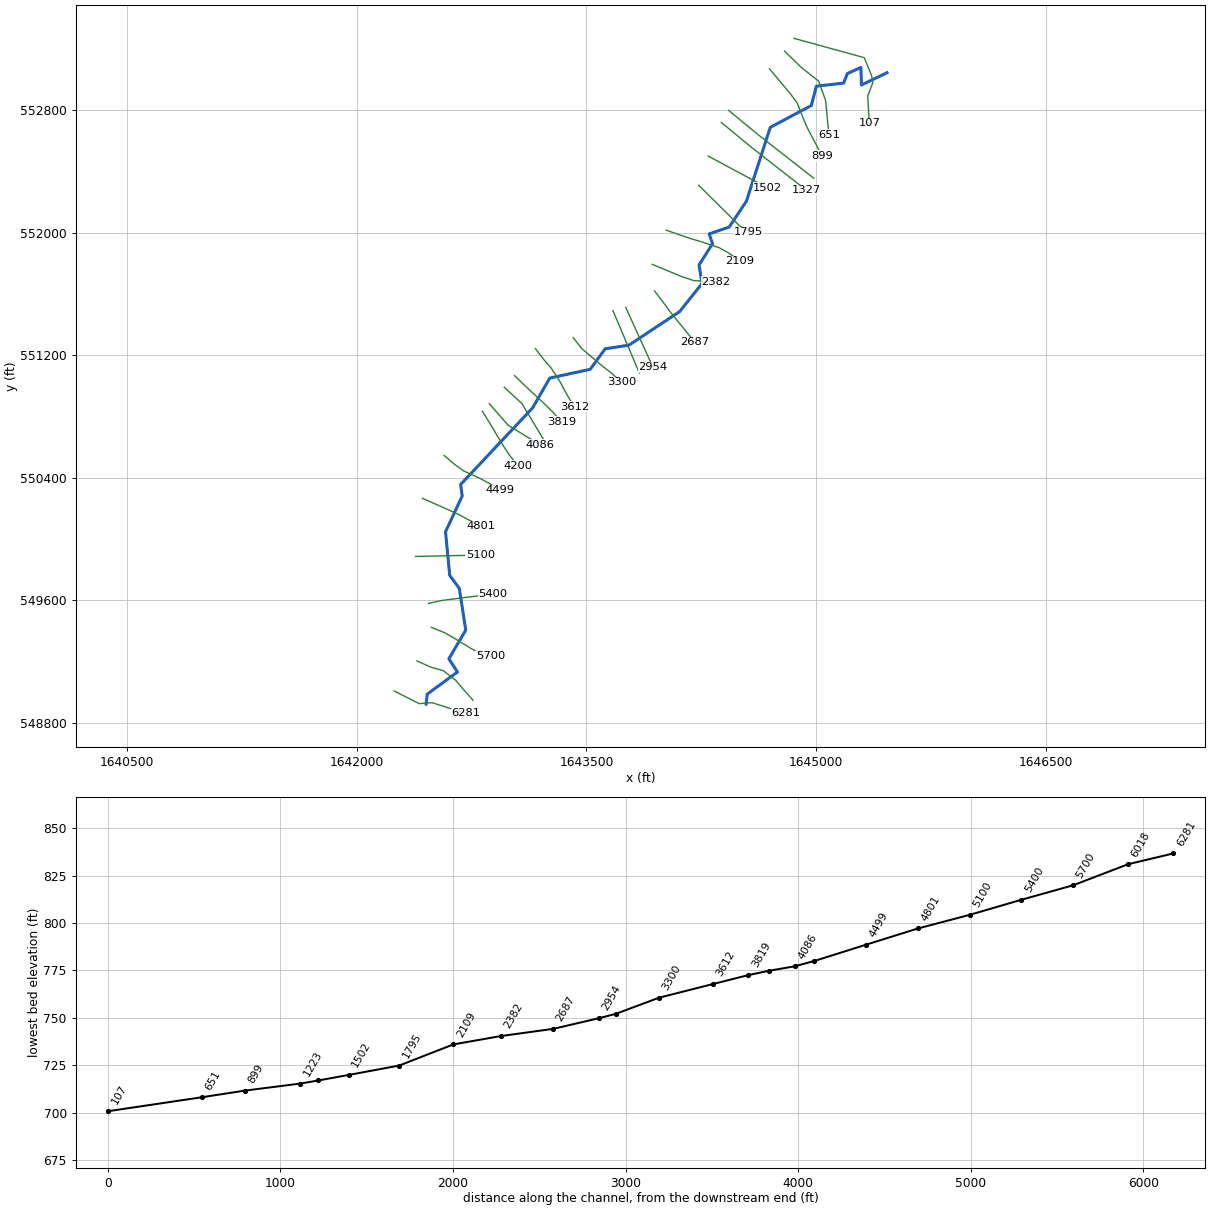
--- WhlingCkT1.prj (project) ---

Proj Title=WhlingCkT1
Current Plan=p01
Default Exp/Contr=0,0
English Units
Geom File=g01
Flow File=f01
Plan File=p01
BEGIN DESCRIPTION:
---------- MODELED AS PART OF WVEM CTP PROGRAM, 2025----------
Stream Name: Wheeling Creek Tributary 1
Flood Zone: AFH
Marshall County, WV
HEC-RAS Version: RAS 6.6
Vertical Datum: NAVD88
Projection: NAD 1983 StatePlane West Virginia N FIPS 4701 (US Feet)
Terrain: 1-meter West Virginia FEMA R3 South Central (collected 2018-2019)
Land Use: 2024 NLCD
Hydrologic Method:
Duda et al., "Estimation of magnitude and frequency of floods for rural, unregulated streams in and near Virginia and West Virginia." September 8, 2025.
Additional Model Notes:
None
END DESCRIPTION:
DSS Export Rating Curves= 0
DSS Export Rating Curve Sorted= 0
DSS Export Volume Flow Curves= 0
DXF OffsetX= 0
DXF OffsetY= 0
DXF ScaleX= 0
DXF ScaleY= 0

--- WhlingCkT1.p01 (plan) ---

Plan Title=Floodplain
Program Version=6.60
Short Identifier=Floodplain
Geom File=g01
Flow File=f01
Subcritical Flow
K Sum by GR= 0
Std Step Tol= 0.01
Critical Tol= 0.01
Num of Std Step Trials= 20
Max Error Tol= 0.3
Flow Tol Ratio= 0.001
Split Flow NTrial= 30
Split Flow Tol= 0.02
Split Flow Ratio= 0.02
Log Output Level= 0
Friction Slope Method= 1
Unsteady Friction Slope Method= 2
Unsteady Bridges Friction Slope Method= 1
Parabolic Critical Depth
Global Vel Dist= 0 , 0 , 0
Global Log Level= 0
CheckData=False
Encroach Param=-1 ,0,0, 0
Flow Ratio Tolerance=0.1
Flow Ratio Min Ratio=0.5
Flow Ratio Max Ratio=4
Flow Ratio Max Iterations= 10
Mapping Interval=1HOUR
Computation Time Step Use Courant=        0
Computation Time Step Use Time Series=    0
Computation Time Step Count To Double=0
Computation Time Step Max Doubling=0
Computation Time Step Max Halving=0
Computation Time Step Residence Courant=0
Run HTab= 0
Run UNet= 0
Run Sediment= 0
Run PostProcess= 0
Run WQNet= 0
Run RASMapper=-1
UNET Theta= 0
UNET Theta Warmup= 0
UNET ZTol= 0
UNET ZSATol= 0
UNET MxIter= 0
UNET Max Iter WO Improvement= 0
UNET MaxInSteps= 0
UNET DtIC= 0
UNET DtMin= 0
UNET MaxCRTS= 0
UNET WFStab= 0
UNET SFStab= 0
UNET WFX= 1
UNET SFX= 1
UNET Gravity=32.17405
UNET 1D Methodology=Finite Difference
UNET DSS MLevel= 1
UNET Pardiso=0
UNET DZMax Abort= 0
UNET Use Existing IB Tables= 0
UNET Froude Reduction=False
UNET Froude Limit= 0
UNET Froude Power= 0
UNET D1 Cores= 0
UNET WindReference=Eulerian
UNET WindDragFormulation=Hsu (1988)
UNET D2 Coriolis=0
UNET D2 Cores= 0
UNET D2 Theta= 1
UNET D2 Theta Warmup= 1
UNET D2 Z Tol= 0.01
UNET D2 Volume Tol= 0.01
UNET D2 Max Iterations= 20
UNET D2 Advanced Convergence=0
UNET D2 WS Max Tol=0.15
UNET D2 WS RMS Tol=0.002
UNET D2 WS Stall Tol=1
UNET D2 Equation= 0
UNET D2 RampUpFraction=0.1
UNET D2 TimeSlices= 1
UNET D2 Turbulence Formulation=Non-Conservative (original)
UNET D2 Eddy Viscosity=0.3
UNET D2 Transverse Eddy Viscosity=0.1
UNET D2 Smagorinsky Mixing=0
UNET D2 BCVolumeCheck=0
UNET D2 Cores=0
UNET D2 SolverType=PARDISO (Direct)
UNET D2 Minimum Iterations= 3
UNET D2 Maximum Iterations= 30
UNET D2 Restart Number= 10
UNET D2 Relaxation Coeff=1.3
UNET D2 SOR Precondition Iterations= 10
UNET D2 ILUT Maximum Fill= 8
UNET D2 ILUT Tolerance=1E-08
UNET D2 Convergence Tolerance=0.00001
PS Theta= 1
PS WS Tol= 0.01
PS Volume Tol= 0.01
PS Max Iterations= 20
PS Equation= 0
PS Advance Time Step=-1
PS Target Courant=0.9
PS Time Slices= 1
PS Iterate With 2D=0
PS Project Initial WSE from DS=-1
PS Ramp Up Initial WSE from US=-1
PS Cores=0
UNET D1D2 MaxIter= 0
UNET D1D2 ZTol=0.01
UNET D1D2 QTol=0.1
UNET D1D2 MinQTol=1
Write IC File= 0
Write IC File at Fixed DateTime=0
Write IC File at Sim End=0
Echo Input=False
Echo Parameters=False
Echo Output=False
Write Detailed= 0
HDF Write Warmup=0
HDF Write Time Slices=0
HDF Flush=0
HDF Compression= 1
HDF Chunk Size= 1
HDF Spatial Parts= 1
HDF Use Max Rows=0
HDF Fixed Rows= 1
Calibration Method= 0
Calibration Iterations= 20
Calibration Max Change=0.05
Calibration Tolerance=0.2
Calibration Maximum=1.5
Calibration Minimum=0.5
Calibration Optimization Method= 1
WQ AD Non Conservative
WQ ULTIMATE=-1
WQ Max Comp Step=1HOUR
WQ Output Interval=15MIN
WQ Output Selected Increments= 0
WQ Create Restart=0
WQ Fixed Restart=0
WQ System Summary=0
WQ Write To DSS=0
Sorting and Armoring Iterations= 10
XS Update Threshold= 0.02
Bed Roughness Predictor= 0
Processes Affected by Predictor=Sediment Only
Hydraulics Update Threshold= 0.02
Energy Slope Method= 1
Volume Change Method= 1
Sediment Retention Method= 0
Sediment TS Multiplier= 1
Warm Up Method= 0
XS Weighting Method= 0
Number of US Weighted Cross Sections= 1
Number of DS Weighted Cross Sections= 1
Upstream XS Weight=0
Main XS Weight=1
Downstream XS Weight=0
Number of DS XS's Weighted with US Boundary= 1
Upstream Boundary Weight= 1
Weight of XSs Associated with US Boundary= 0
Number of US XS's Weighted with DS Boundary= 1
Downstream Boundary Weight= 0.5
Weight of XSs Associated with DS Boundary= 0.5
Percentile Method= 0
Sediment Output Level= 3
Mass or Volume Output= 0
Output Increment Type= 1
Profile and TS Output Increment= 1
Transport Output Increment 1
XS Output Flag= 0
XS Output Increment= 10
Read HDF5 Sediment Hotstart= 0
Sediment Hotstart Type= 0
Write Gradation File= 0
Read Gradation Hotstart= 0
Write HDF5 File= 1
Write Binary Output= 1
Write DSS Sediment File= 0
DSS Sediment Output Type= 1
SV Curve= 0
Specific Gage Flag= 0
Subcell Erosion Methods= 0
Subcell Deposition Methods= 0
Advection Scheme= 1
Matrix Solver= 0
Implicit Weighting Factor= 1
Maximum Outer Loop Convergence Iterations= 5
Convergence Maximum Absolute= 0.001
Convergence RMSE= 0.0001
Grain Fractions Max Abs Error= 0.001
Max Subgrid Regions= 1
Max Subgrid Length Scale= 3.402823E+38
Initial Layer Thickness= 3
Min Layer Thickness= 0.1
Max Layer Thickness= 6
Number of Layers= 5

--- WhlingCkT1.f01 (steady flow) ---

Flow Title=Flow
Program Version=6.60
Number of Profiles= 1
Profile Names=P100yr
River Rch & RM=WhlingCkT1,Main,6281
     829
River Rch & RM=WhlingCkT1,Main,3300
     931
Boundary for River Rch & Prof#=WhlingCkT1,Main            , 1
Up Type= 0
Dn Type= 3
Dn Slope=0.026942
DSS Import GetInterval= 0
DSS Import GetPeak= 0
DSS Import FillOption= 0

--- WhlingCkT1.g01 (geometry) ---

Geom Title=Geometry
Program Version=6.60

River Reach=WhlingCkT1      ,Main
Reach XY= 30
     1642453.289      548921.465      1642460.21      548986.657
     1642658.017      549131.328     1642601.533      549217.505
     1642711.822      549404.372     1642670.073      549676.523
     1642606.891      549763.147     1642579.779      550046.963
     1642688.617      550280.686     1642678.501      550356.035
     1643148.068      550855.681     1643260.518      551050.718
      1643525.15      551108.274      1643622.49      551242.229
     1643777.208      551265.671     1644108.745       551484.91
     1644254.756      551668.428      1644235.58       551789.83
     1644323.693      551928.747     1644301.435      551992.282
     1644432.508      552037.244     1644544.323      552204.828
     1644700.588      552688.296     1644968.566      552830.643
     1645001.881      552957.059     1645180.439      552977.776
     1645203.856      553039.542     1645292.693      553079.588
     1645296.176      552965.043      1645463.23      553045.278

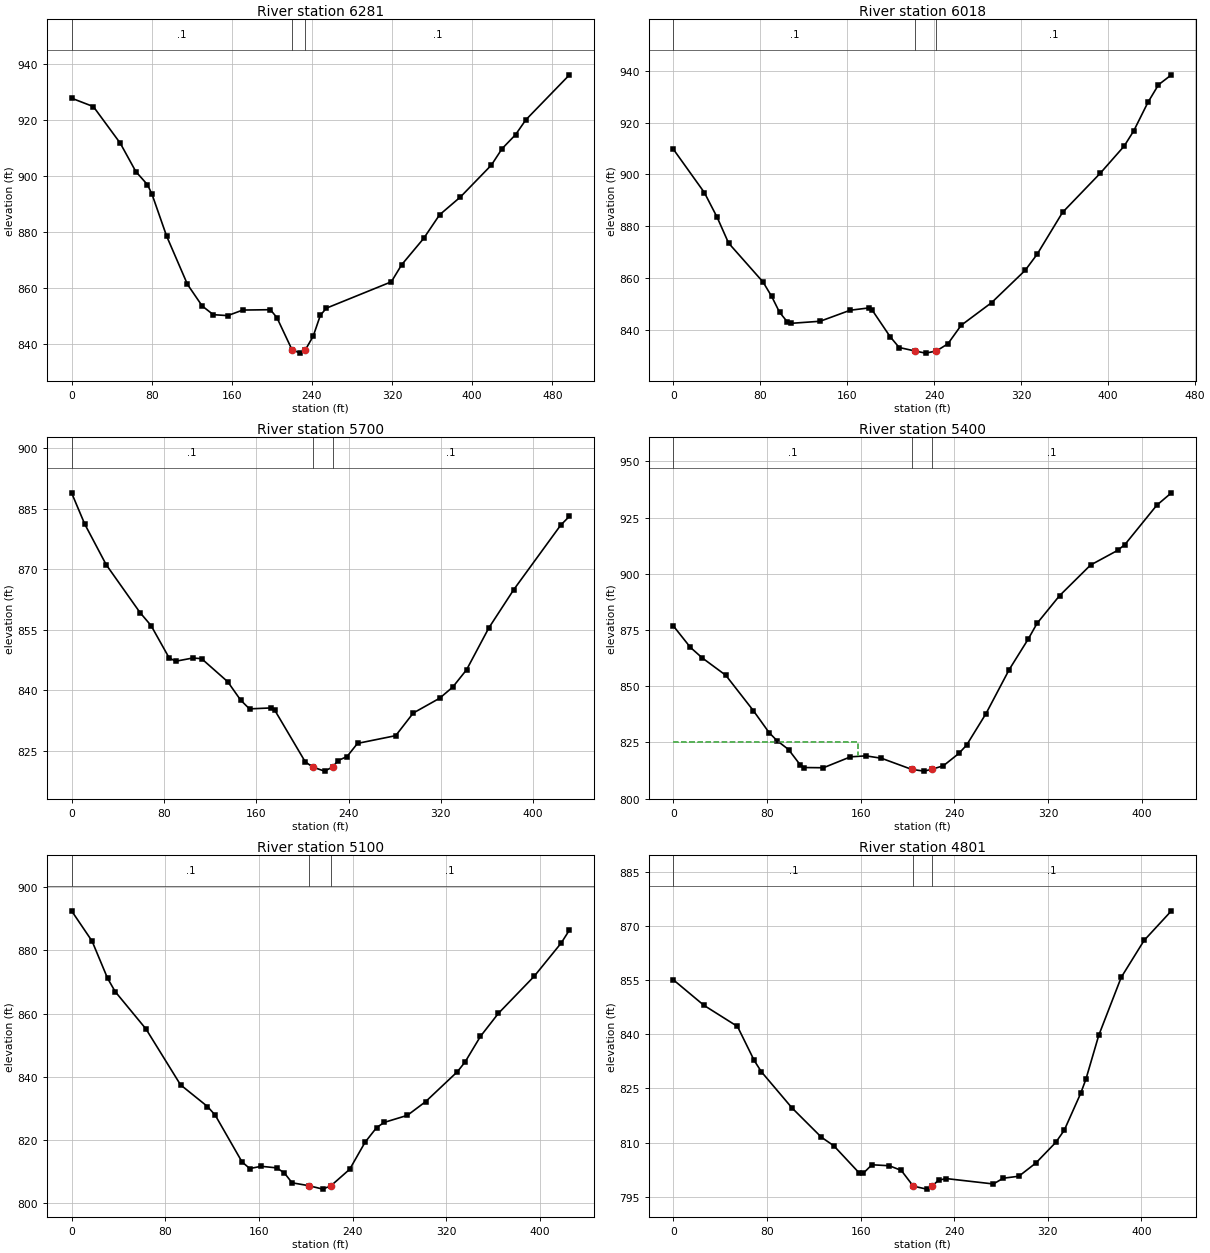
Type RM Length L Ch R = 1 ,6281    ,265.1,262.7,256.4
XS GIS Cut Line= 4
1642245.26495774  549007.20106821642407.70077095548924.573669893
 1642491.5166423548930.8993960321642711.53349486548861.023378081
#Sta/Elev= 30
       0  927.81    21.8   924.8    48.6  911.73    64.2  901.57    75.8  896.89
    80.3  893.49    94.9  878.52   115.7  861.27   130.4  853.55   141.5  850.44
   155.9  850.11   170.9  852.09   198.5  852.22     205  849.39  220.03837.9459
   228.1   836.7  233.48 837.944   241.2  842.73   248.4  850.25   254.4  852.77
   319.2  862.18   329.6  868.31   351.5  877.69   367.4  886.13   388.2   892.5
   419.1   903.9   429.8  909.77   443.2  914.75   453.5  920.07   497.1  936.16
#Mann= 3 ,-1,0
       0      .1       0  220.03    .045       0  233.48      .1       0
Bank Sta=220.03,233.48
XS Rating Curve= 0 ,0
Exp/Cntr=0.3,0.1

Type RM Length L Ch R = 1 ,6018    ,312.8,318,316
XS GIS Cut Line= 6
 1642393.7173771549203.2099619211642484.61450501549162.739570424
1642566.21867251549139.3308245841642647.19357617549076.292564839
1642698.68002176549015.0571230051642759.20844401548946.852863088
#Sta/Elev= 30
       0  909.68    28.4  893.02    40.2  883.44    50.7  873.51    82.4  858.48
    90.4  852.88    97.6  846.79   104.6  843.16   108.4  842.52     135  843.32
   162.6  847.57   179.7  848.46   183.1  847.47   199.4  837.34   207.7  833.18
  222.29831.8315     232  831.01   241.9831.8317   252.5   834.6   264.7  841.74
   292.8  850.53   323.6  862.96   334.7  869.23     358  885.34   392.8  900.51
   414.7  910.94   423.5  916.81   436.6  927.84   446.3  934.63   458.2  938.47
#Mann= 3 ,-1,0
       0      .1       0  222.29    .045       0   241.9      .1       0
Bank Sta=222.29,241.9
XS Rating Curve= 0 ,0
Exp/Cntr(USF)=0,0
Exp/Cntr=0.3,0.1

Type RM Length L Ch R = 1 ,5700    ,294.3,300.3,306
XS GIS Cut Line= 6
1642487.88648009549422.4470562491642573.41682084549387.992400751
1642638.63256967549350.8438530121642723.79578517549298.425322667
1642788.54598376 549260.517918171642873.97002551549234.992378667
#Sta/Elev= 30
       0  888.94    11.4   881.2      30  871.12    59.3  859.25    68.9  856.01
    84.5  848.03    90.1  847.16   105.1  847.97   112.7   847.8   135.3  842.09
   146.6   837.5   154.2  835.35   173.2  835.59   176.2  834.97   202.5  822.22
     209820.9189   219.2  819.91  226.18820.9177     231  822.54   238.7  823.52
   247.8  826.79   280.9  828.71   296.1  834.32   318.9  837.98   330.3  840.75
   342.3  845.05   361.6  855.44   383.2  864.93   423.9  880.93   431.5  883.13
#Mann= 3 ,-1,0
       0      .1       0     209    .045       0  226.18      .1       0
Bank Sta=209,226.18
XS Rating Curve= 0 ,0
Exp/Cntr(USF)=0,0
Exp/Cntr=0.3,0.1

Type RM Length L Ch R = 1 ,5400    ,300.4,300,298.2
XS GIS Cut Line= 6
  1642468.878316549579.0592758361642554.62880068549598.388633505
1642629.03613217549607.8410424291642728.24656367549620.384980589
1642802.64306842549629.836077169 1642889.4427636549640.862957999
#Sta/Elev= 30
       0  876.77    14.4  867.32    24.5  862.64    44.7  854.88    68.2  839.19
    81.7  829.39    88.4  825.84    98.3  821.87   108.2   815.1   111.5  813.86
   128.1  813.76   151.2  818.61   164.4  819.05   177.7  817.98  203.55 813.035
     214  812.26  220.45 813.037   230.6  814.65   243.8  820.12   250.4  823.82
     267  837.84   286.8   857.4   303.1  871.01   310.6  877.96   329.8  890.26
   356.3   903.9   379.4  910.41   385.7  913.04   412.9  930.51   425.4  936.02
#Mann= 3 ,-1,0
       0      .1       0  203.55    .045       0  220.45      .1       0
#XS Ineff= 2 , 0
          157.76  825.42
Permanent Ineff=
       F       F
Bank Sta=203.55,220.45
XS Rating Curve= 0 ,0
Exp/Cntr(USF)=0,0
Exp/Cntr=0.3,0.1

Type RM Length L Ch R = 1 ,5100    ,302.3,299.3,294.9
XS GIS Cut Line= 6
1642383.35748968549885.7712608431642470.83664542549887.670535252
1642545.81910701549889.298484758 1642645.7956131549891.469084084
1642720.77807467549893.0973616691642808.25723043 549894.99597992
#Sta/Elev= 30
       0  892.58    17.5  882.97    30.7  871.21    37.2  866.97    63.5  855.11
      93  837.39     116  830.51   122.6  827.77   145.5  812.93   152.1  810.83
   161.9  811.54   175.1  811.04   181.6  809.44   188.2  806.31  202.95  805.36
   214.4   804.3  221.35805.3594   237.4   810.6   250.5  819.16   260.4  823.84
   266.9  825.47   286.6   827.7   302.2  832.05   329.3  841.54   335.9  844.64
     349  852.76   364.3  860.05   394.9  871.83   417.9  882.36     425  886.52
#Mann= 3 ,-1,0
       0      .1       0  202.95    .045       0  221.35      .1       0
Bank Sta=202.95,221.35
XS Rating Curve= 0 ,0
Exp/Cntr(USF)=0,0
Exp/Cntr=0.3,0.1

Type RM Length L Ch R = 1 ,4801    ,299.5,301.3,299.5
XS GIS Cut Line= 6
 1642429.6110061550265.2196489271642509.67613468550229.923131585
  1642578.303294550199.6689269991642669.25816458550158.087317258
1642735.52607667550122.4817454221642813.82349226550082.519226924
#Sta/Elev= 30
       0  855.01      26  847.99    54.7  842.14      69  832.73    75.1  829.61
   101.3   819.6   126.4   811.5   137.1  809.11   158.7  801.62   162.2  801.51
   169.6  803.87   184.5   803.6   194.7  802.31  204.94 797.962   216.4  797.13
  221.01797.9651   226.6  799.61   233.1  800.05   273.4  798.56   281.9  800.15
   295.2   800.7   309.7  804.34   326.7  810.04     334  813.42     348  823.59
   352.5  827.52   363.5  839.69   382.7  855.73   402.3  865.96   425.6  874.13
#Mann= 3 ,-1,0
       0      .1       0  204.94    .045       0  221.01      .1       0
Bank Sta=204.94,221.01
XS Rating Curve= 0 ,0
Exp/Cntr(USF)=0,0
Exp/Cntr=0.3,0.1

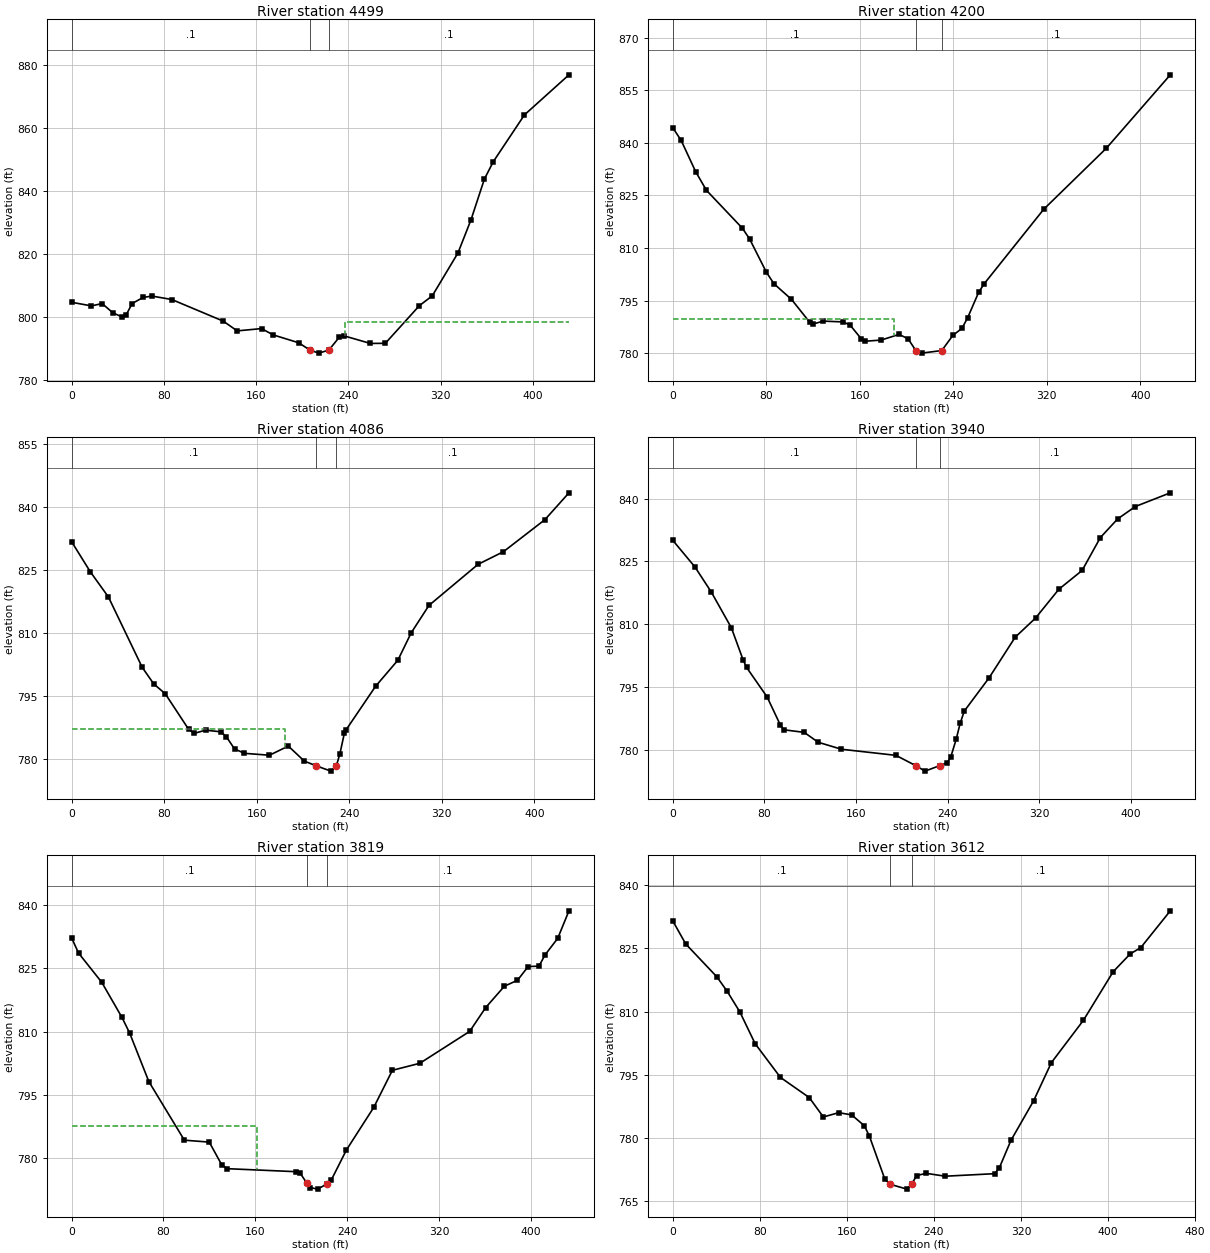
Type RM Length L Ch R = 1 ,4499    ,302.4,299.3,289.8
XS GIS Cut Line= 6
1642570.82069743550545.0445485861642638.45146768550487.682130501
1642700.09504518550443.2816287581642791.85371992550402.211172834
  1642859.700369550366.6466114221642935.56275009550319.397362083
#Sta/Elev= 30
       0   804.7    17.3  803.55    26.5   804.3    35.9  801.34    43.9  800.03
    47.5  800.78    52.5   804.3      62  806.23    69.7  806.67    86.9  805.58
   131.5  798.72   143.6  795.62   164.7  796.35   174.7  794.36   196.9  791.85
  206.62789.5341   214.3  788.56  223.11789.5359   232.2  793.65   235.8  794.09
     259  791.64     272  791.67   301.6  803.65   312.7  806.74     335  820.37
   346.3   830.9   357.9  843.82   365.6  849.33   392.6  864.18   431.2   876.9
#Mann= 3 ,-1,0
       0      .1       0  206.62    .045       0  223.11      .1       0
#XS Ineff= 2 , 0
                          236.82          798.44
Permanent Ineff=
       F       F
Bank Sta=206.62,223.11
XS Rating Curve= 0 ,0
Exp/Cntr(USF)=0,0
Exp/Cntr=0.3,0.1

Type RM Length L Ch R = 1 ,4200    ,110.3,114.1,119.6
XS GIS Cut Line= 6
1642820.41632684 550834.466870011642866.40540808550760.018528089
1642904.99292934550695.7066488421642956.44262959550609.957476512
1642997.50816426   550547.132799  1643053.640926550479.150323421
#Sta/Elev= 30
       0  844.29     7.1  840.68    19.5  831.78    28.7  826.46    59.5  815.63
    65.7  812.55      80  803.09    86.5  799.79   101.5  795.32   117.1   788.8
   120.1  788.29   128.6  789.12   145.6  788.89   151.6  788.01   161.3  784.04
   164.7  783.38   178.3  783.71   193.6  785.33   201.3  784.07  207.93780.7126
   212.8  779.98  230.11780.7144   239.6  785.03   247.4  787.06   252.2  790.02
   261.7  797.35   266.5  799.82   317.4  821.05     371  838.48   425.7  859.42
#Mann= 3 ,-1,0
       0      .1       0  207.93    .045       0  230.11      .1       0
#XS Ineff= 2 , 0
          189.53  789.61
Permanent Ineff=
       F       F
Bank Sta=207.93,230.11
XS Rating Curve= 0 ,0
Exp/Cntr(USF)=0,0
Exp/Cntr=0.3,0.1

Type RM Length L Ch R = 1 ,4086    ,149.9,146.5,140.5
XS GIS Cut Line= 3
1642865.92262437550883.2747190021642988.35178235550743.256528058
1643196.19581468550615.362645547
#Sta/Elev= 30
       0  831.86    16.2  824.68    31.9  818.65    61.1  801.89    71.1  797.94
      81  795.61   101.3   787.1     106  786.16   115.9  786.93   129.2  786.53
   133.9  785.33   140.9  782.46   149.5  781.41   171.1  780.96   187.4  783.14
   201.2  779.57  211.58778.4161   224.3  777.17  228.91778.4135     232  781.31
   235.9  786.27   237.4  787.04   262.8  797.37   282.1   803.6   293.6  810.11
     309  816.66   351.4  826.44   373.4  829.46   409.2  837.08     430  843.48
#Mann= 3 ,-1,0
       0      .1       0  211.58    .045       0  228.91      .1       0
#XS Ineff= 2 , 0
          184.48  787.21
Permanent Ineff=
       F       F
Bank Sta=211.58,228.91
XS Rating Curve= 0 ,0
Exp/Cntr(USF)=0,0
Exp/Cntr=0.3,0.1

Type RM Length L Ch R = 1 ,3940    ,118.5,120.8,124.6
XS GIS Cut Line= 3
 1642963.7661337550990.4553135151643079.05825099550884.094275733
1643221.95552313550646.202794281
#Sta/Elev= 30
       0     830    19.3  823.65    33.5  817.69    51.1  809.12    61.3  801.47
    64.4  799.64    82.3  792.59    93.8  785.92    96.7  784.76   114.7  784.13
   126.9  781.77   147.2   780.1   194.8  778.64     212 776.195   220.2  774.87
     233  776.18   239.4  776.85   242.6  778.17   247.4  782.47   250.9  786.31
   254.5  789.23   276.1  797.15   298.9  806.86   316.7  811.45   337.1  818.34
   357.4  822.83   373.3  830.68   388.4  835.14   403.9  838.11   434.4  841.38
#Mann= 3 ,-1,0
       0      .1       0     212    .045       0     233      .1       0
Bank Sta=212,233
XS Rating Curve= 0 ,0
Exp/Cntr(USF)=0,0
Exp/Cntr=0.3,0.1

Type RM Length L Ch R = 1 ,3819    ,209.8,206.7,205.7
XS GIS Cut Line= 6
1643030.77182066 551067.046152611643095.55909266551003.906187016
1643152.95989649550950.8495346041643227.47779208550881.430382106
1643280.51049441550828.3973516861643340.32238266550764.536587018
#Sta/Elev= 30
       0  832.28     6.2  828.62    26.3  821.71    43.8  813.41    50.5  809.71
    67.3  798.12    98.2   784.2   119.9  783.74   130.7  778.36   135.4  777.43
   195.7  776.71     199  776.37     205  773.92     208  772.93   214.3  772.57
  222.74  773.88   225.9  774.62   239.3  781.88   263.1     792   279.3   800.8
   303.2  802.47   346.6  810.05   360.5   815.7   376.8  820.78   388.2  822.19
   397.5  825.46   406.9  825.54   412.1  828.19   423.2  832.14     433  838.69
#Mann= 3 ,-1,0
       0      .1       0     205    .045       0  222.74      .1       0
#XS Ineff= 2 , 0
          161.39  787.59
Permanent Ineff=
       F       F
Bank Sta=205,222.74
XS Rating Curve= 0 ,0
Exp/Cntr(USF)=0,0
Exp/Cntr=0.3,0.1

Type RM Length L Ch R = 1 ,3612    ,309.6,311.9,317.2
XS GIS Cut Line= 6
1643167.18630259 551242.704898671643220.50771825551172.994408175
1643269.83439125551116.3655844181643327.37233393551027.690236837
1643369.41129184550948.7645416711643419.83770017550863.337875262
#Sta/Elev= 30
       0  831.49    11.8  826.05    40.5  818.22    49.9   814.8    61.6  809.89
    75.6  802.36    98.9  794.34   125.3  789.57   138.3  784.95   152.4  785.97
   164.3  785.45     176  782.86   180.7  780.35   194.9  770.12  199.87768.9507
   215.1  767.81  219.42768.9532     224  771.03   232.8  771.56   250.3  770.88
   295.8  771.48     300  772.83   310.7  779.37   331.5  788.76   347.9  797.86
   377.3   807.9   404.7  819.46   420.4   823.7     430  825.16   457.2  833.92
#Mann= 3 ,-1,0
       0      .1       0  199.87    .045       0  219.42      .1       0
Bank Sta=199.87,219.42
XS Rating Curve= 0 ,0
Exp/Cntr(USF)=0,0
Exp/Cntr=0.3,0.1

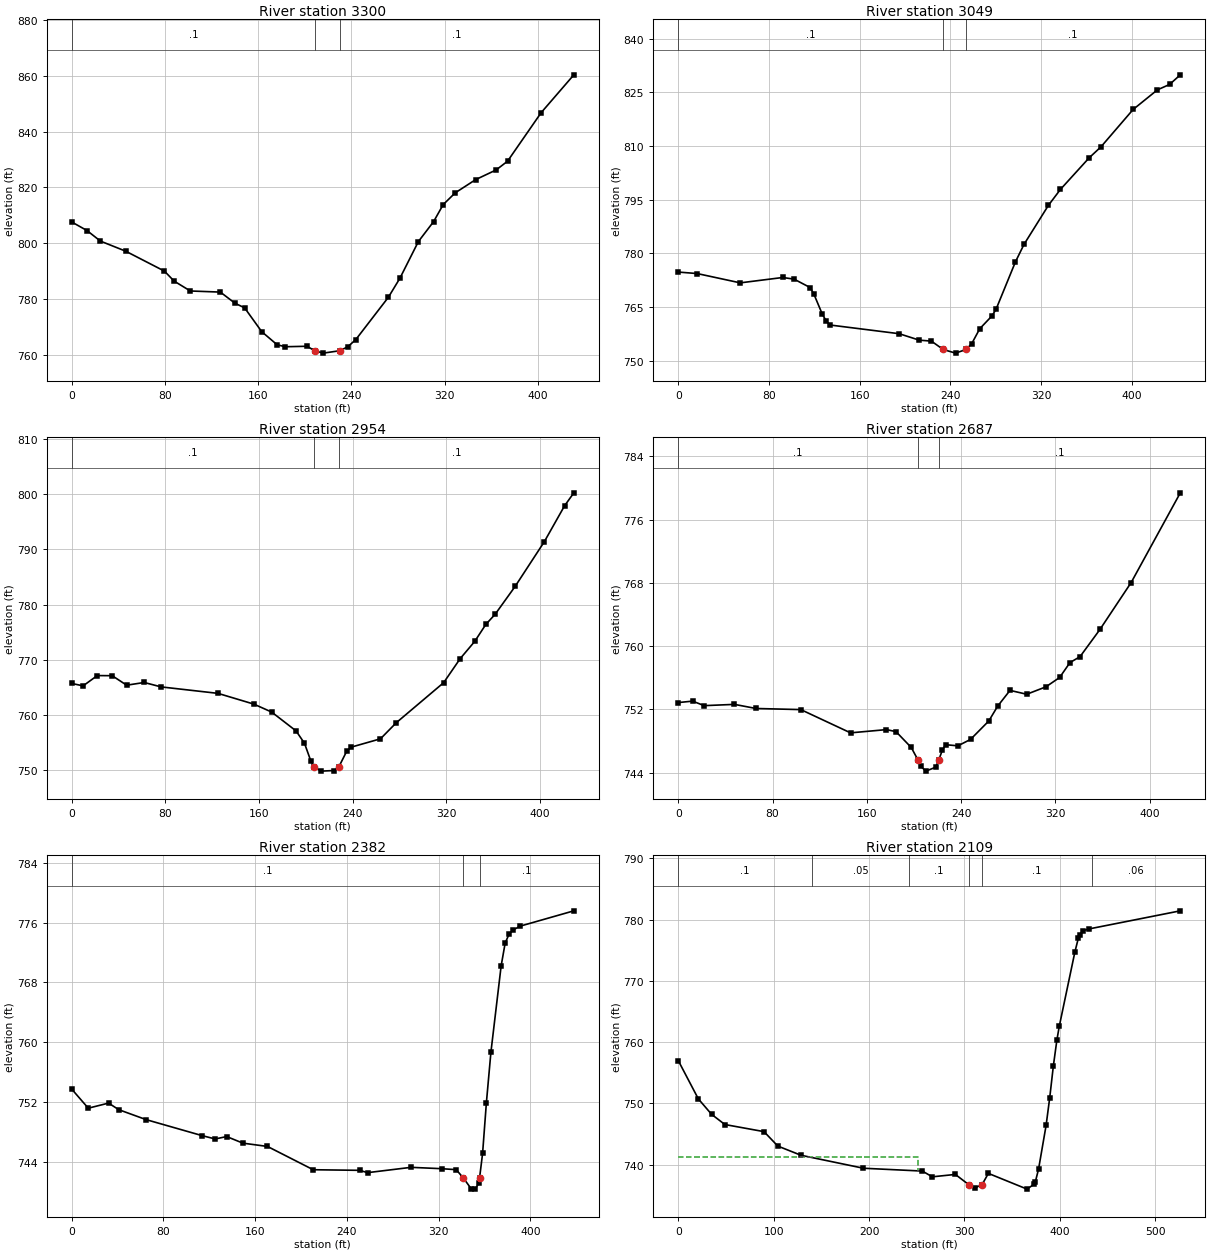
Type RM Length L Ch R = 1 ,3300    ,253.5,250.7,244.2
XS GIS Cut Line= 6
1643413.23797584551315.6643984171643469.63320425 551243.36040917
1643526.77843118551194.7870155131643602.97283259 551130.02270934
1643662.71352676551084.4617768381643727.98504975551024.007829502
#Sta/Elev= 30
       0  807.63      13  804.58    24.6  800.78    46.2  797.18    79.5  790.02
    87.8  786.45   101.7   782.9   127.5   782.5   140.1  778.49   148.3  776.86
     163  768.31   176.2  763.62   183.2  762.91   201.8  763.08  208.61761.4692
   215.8  760.62  229.76761.4697   236.7  762.86   243.7  765.47   271.7  780.67
   281.6   787.5   297.4  800.62   310.5  807.79   318.7  813.87     329  818.08
   346.5  822.81   364.2  826.31   373.9  829.42   402.8  846.85   430.8  860.39
#Mann= 3 ,-1,0
       0      .1       0  208.61    .045       0  229.76      .1       0
Bank Sta=208.61,229.76
XS Rating Curve= 0 ,0
Exp/Cntr(USF)=0,0
Exp/Cntr=0.3,0.1

Type RM Length L Ch R = 1 ,3049    ,92.8,95.2,93.2
XS GIS Cut Line= 2
1643673.39278031551491.458144362 1643845.7688176551083.448808385
#Sta/Elev= 30
       0  774.77    16.7  774.35    54.7  771.75    92.2  773.25   102.2  772.79
   116.4  770.43   119.8   768.5   127.1  762.98   130.7  760.99   134.2  759.95
   194.9  757.53   212.6  755.73   223.3  755.46  233.72753.1227   244.6   752.1
  253.91753.1219   258.9  754.75     266  758.93   276.7  762.49   280.3  764.32
   297.5  777.65     305  782.49   326.6  793.45   337.2   797.9   362.6  806.75
   372.9  809.78   401.3  820.24   422.7  825.72   433.4  827.22   442.9  829.92
#Mann= 3 ,-1,0
       0      .1       0  233.72    .045       0  253.91      .1       0
Bank Sta=233.72,253.91
XS Rating Curve= 0 ,0
Exp/Cntr(USF)=0,0
Exp/Cntr=0.3,0.1

Type RM Length L Ch R = 1 ,2954    ,264.8,267.2,269.5
XS GIS Cut Line= 2
1643756.67700075551512.7311302421643934.13686842551122.234667167
#Sta/Elev= 30
       0  765.74     9.7  765.31    21.8  767.17    34.5  767.15    46.9  765.43
    61.9  765.92    76.3  765.12   124.9  763.95   155.6     762   170.8  760.56
   191.6  757.15   198.8  754.91   204.2  751.72  206.86750.6344   213.2  749.87
     224  749.98  228.14750.6334   234.9  753.49   238.5   754.2   263.7  755.72
   277.3  758.65   317.7  765.89   331.8  770.24   344.2  773.35   353.8  776.46
   361.6  778.25   378.7   783.3   403.7  791.42     421  797.92   428.9  800.26
#Mann= 3 ,-1,0
       0      .1       0  206.86    .045       0  228.14      .1       0
Bank Sta=206.86,228.14
XS Rating Curve= 0 ,0
Exp/Cntr(USF)=0,0
Exp/Cntr=0.3,0.1

Type RM Length L Ch R = 1 ,2687    ,298.7,304.6,311.1
XS GIS Cut Line= 6
1643944.72915209 551620.30176928 1643998.3176276551550.366869786
1644042.57410075551489.3669917821644105.37974942551411.549890199
1644152.61554735551353.2937731231644207.72370485 551285.32802979
#Sta/Elev= 30
       0  752.87    12.2  753.05      22  752.48    47.7  752.64      66  752.12
     104  751.98   146.2  749.04   176.7  749.45   184.8  749.19   197.7  747.19
   203.2  745.67   205.8  744.81   210.1   744.2   218.5   744.7     221  745.59
   224.1  746.86   226.9  747.54   237.3   747.4     248  748.21   263.5  750.54
   271.1  752.43   281.5  754.41   295.7  753.92     312  754.86   323.6  756.04
   332.4  757.93   340.9  758.67   357.8  762.11   384.3  768.05     426  779.39
#Mann= 3 ,-1,0
       0      .1       0   203.2    .045       0     221      .1       0
Bank Sta=203.2,221
XS Rating Curve= 0 ,0
Exp/Cntr(USF)=0,0
Exp/Cntr=0.3,0.1

Type RM Length L Ch R = 1 ,2382    ,274.2,273.6,270.7
XS GIS Cut Line= 4
1643929.61403132551793.647135775  1644118.658481551715.191814587
1644201.53659609551687.3657547531644347.17127147551679.697152641
#Sta/Elev= 30
       0  753.74    14.4   751.2    32.1  751.88      41     751    64.9  749.67
   113.8  747.53   125.1  747.09   135.1  747.41   149.3  746.53   170.7  746.09
   210.6  742.98   251.1   742.9     258  742.59   295.9   743.3   322.5  743.12
   335.3  742.99  341.61741.8649   348.5  740.41   351.8  740.39   355.1  741.19
  355.66741.8667   358.3  745.15   361.6   751.9   365.6  758.72   374.5  770.22
     378  773.26   381.3  774.41   384.6  774.98   391.2  775.52   437.9  777.56
#Mann= 3 ,-1,0
       0      .1       0  341.61    .045       0  355.66      .1       0
Bank Sta=341.61,355.66
XS Rating Curve= 0 ,0
Exp/Cntr(USF)=0,0
Exp/Cntr=0.3,0.1

Type RM Length L Ch R = 1 ,2109    ,310,313.7,303.1
XS GIS Cut Line= 6
 1644021.3588911552016.5700202611644174.82667576551963.712643012
1644257.65525025551938.9088868351644366.43587258551902.639602423
1644431.82091242 551865.861460761644503.01204301551814.404870749
#Sta/Elev= 30
       0     757    21.1  750.73      35  748.21    48.9  746.55    89.9  745.39
   104.4  743.03   128.7  741.53   194.2  739.41   255.9  738.95   266.3  738.01
   290.5   738.4  304.41736.7461   311.4  736.22  318.53  736.75   325.1  738.57
   365.7     736   372.9   736.8   374.4  737.24   377.7  739.26   385.6   746.4
   389.4  750.91   393.2   756.1   396.9  760.33   399.4  762.58   415.8  774.74
   419.5  777.04   421.1  777.57   423.8  778.19   430.8   778.5   526.3  781.45
#Mann= 6 ,-1,0
       0      .1       0     140     .05       0  242.32      .1       0
  304.41    .045       0  318.53      .1       0  433.45     .06       0
#XS Ineff= 2 , 0
          251.26  741.31
Permanent Ineff=
       F       F
Bank Sta=304.41,318.53
XS Rating Curve= 0 ,0
Exp/Cntr(USF)=0,0
Exp/Cntr=0.3,0.1

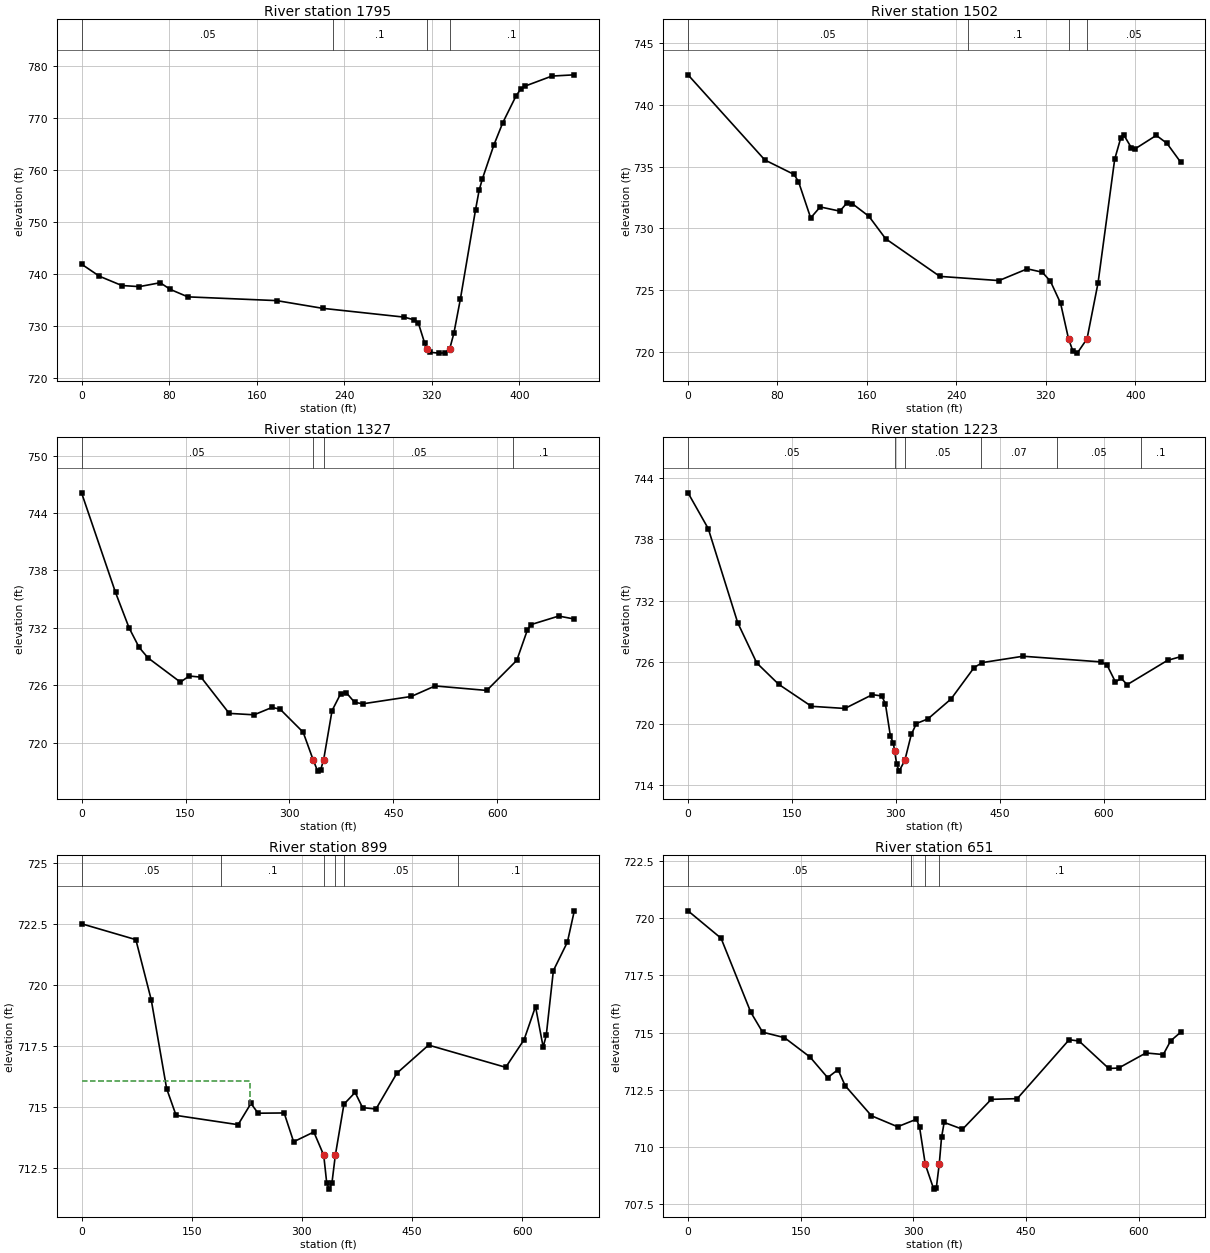
Type RM Length L Ch R = 1 ,1795    ,289.9,293.2,295.8
XS GIS Cut Line= 3
1644233.15564016 552310.514736421644498.65739292552046.625534922
1644560.22387084552002.459284678
#Sta/Elev= 30
       0  741.98    16.3  739.66    36.8  737.87    52.8  737.66    71.8  738.41
    81.1  737.12    97.1  735.69   178.2  734.97   220.1  733.49   294.8  731.79
   304.1  731.25   307.7  730.62   313.4   726.8  315.57725.7184     318  725.04
   326.2  724.87     332  724.92  336.32725.7173   340.1  728.71     346  735.23
   359.9  752.47   363.2  756.22   366.2  758.43   376.7  764.94   384.8   769.2
   396.9  774.34     401  775.61     405  776.21   429.6  778.15   450.1  778.39
#Mann= 4 ,-1,0
       0     .05       0     230      .1       0  315.57    .045       0
  336.32      .1       0
Bank Sta=315.57,336.32
XS Rating Curve= 0 ,0
Exp/Cntr(USF)=0,0
Exp/Cntr=0.3,0.1

Type RM Length L Ch R = 1 ,1502    ,177.2,175.3,175.1
XS GIS Cut Line= 2
1644295.69911238552500.7118325871644683.97741156552292.148619627
#Sta/Elev= 30
       0  742.42    68.7  735.53    94.8  734.36    98.8  733.78   109.7  730.84
   118.2  731.73   135.8  731.39   142.4  732.08     147  731.99   161.8  730.97
   176.7  729.16   225.2  726.11   278.1  725.77   303.4  726.72   316.8  726.45
   324.1  725.72   333.2  723.94   340.3721.0587   344.3  720.04   348.1   719.9
  356.86721.0569   366.7  725.58   381.6  735.59   387.1  737.34   389.5  737.59
   396.5  736.52   400.2  736.45   418.8  737.52   428.3  736.88   440.7  735.34
#Mann= 4 ,-1,0
       0     .05       0     250      .1       0   340.3    .045       0
  356.86     .05       0
Bank Sta=340.3,356.86
XS Rating Curve= 0 ,0
Exp/Cntr(USF)=0,0
Exp/Cntr=0.3,0.1

Type RM Length L Ch R = 1 ,1327    ,102.6,103.9,103
XS GIS Cut Line= 3
1644380.76571818552720.4941177151644575.94479685552559.604758651
1644936.71678221552277.574838874
#Sta/Elev= 30
       0  746.12      49   735.7    68.6  731.99      83  729.96    95.8  728.86
   142.6  726.32   155.3  726.96   172.3  726.84     213  723.05   248.9   722.9
   274.7  723.67   286.3   723.5   319.7  721.08  333.95 718.225   340.6  717.01
   344.8   717.1  349.31 718.224   361.4  723.34   373.9  725.12   382.2  725.19
   393.9  724.21   405.6  724.05   475.7  724.82     510  725.92   584.6  725.45
   627.9   728.6   643.2  731.77   648.6  732.34   688.4  733.23   710.9  732.92
#Mann= 4 ,-1,0
       0     .05       0  333.95    .045       0  349.31     .05       0
  622.94      .1       0
Bank Sta=333.95,349.31
XS Rating Curve= 0 ,0
Exp/Cntr(USF)=0,0
Exp/Cntr=0.3,0.1

Type RM Length L Ch R = 1 ,1223    ,325.9,323.3,318.3
XS GIS Cut Line= 3
1644428.86159368552799.0278185671644624.04067235552638.138459504
1644984.81265771552356.108539727
#Sta/Elev= 30
       0  742.55    29.2  739.05    71.7  729.86    99.2  725.93   130.8  723.85
     178   721.7   226.3  721.49     266  722.84   279.5  722.71   284.7  721.96
     292  718.78   296.2  718.12298.0411717.3355     301  716.07   304.5  715.37
312.7462716.4092   322.1  718.95   329.5  720.02   346.1  720.47   379.5  722.42
   412.8  725.49   424.5  725.97   483.3  726.59   595.5  726.04   604.3  725.76
   616.6  724.08   625.1  724.43   633.5  723.81   691.8  726.19   710.9  726.55
#Mann= 6 ,-1,0
       0     .05       0298.0411    .045       0312.7462     .05       0
  422.94     .07       0  532.94     .05       0  652.94      .1       0
Bank Sta=298.0411,312.7462
XS Rating Curve= 0 ,0
Exp/Cntr(USF)=0,0
Exp/Cntr=0.3,0.1

Type RM Length L Ch R = 1 ,899     ,248.3,247.9,245.8
XS GIS Cut Line= 6
1644695.39544263553070.8705671441644830.53074493552909.269150838
1644876.66582325552848.1984068451644912.96037009552754.929564506
1644942.17979984552685.5757005961645039.77075287 552501.64766566
#Sta/Elev= 30
       0   722.5    73.9  721.85    94.9  719.38   115.8  715.75   128.7  714.65
   213.1  714.27   230.6  715.14   240.3  714.74   275.8  714.75   288.7  713.57
   316.2  713.97  329.67713.0195   333.8  711.87   337.3  711.63   340.8  711.87
   345.5  713.02   357.2  715.11   372.4  715.59   382.5  714.97   400.8  714.91
   429.3  716.38   472.4  717.53   577.4  716.62   602.4  717.75     618  719.11
   628.4  717.45   632.6  717.93   642.3  720.58   661.4  721.75   670.8  723.03
#Mann= 6 ,-1,0
       0     .05       0     190      .1       0  329.67    .045       0
   345.5      .1       0   357.2     .05       0  512.54      .1       0
#XS Ineff= 2 , 0
          228.95  716.06
Permanent Ineff=
       F       F
Bank Sta=329.67,345.5
XS Rating Curve= 0 ,0
Exp/Cntr(USF)=0,0
Exp/Cntr=0.3,0.1

Type RM Length L Ch R = 1 ,651     ,541.5,544.4,533.4
XS GIS Cut Line= 5
1644793.83041326553186.6515223461644900.97003764553081.764176675
1645016.73632854552990.2279240011645062.52925539 552862.03399962
1645083.40837546552640.467076882
#Sta/Elev= 30
       0  720.33      44  719.13    83.6  715.89    99.3  715.02   128.4  714.78
   162.5  713.93   185.9  713.03   199.8  713.38   209.2  712.68   244.3  711.36
   279.1  710.88   304.2  711.21   308.3  710.87     316  709.23   327.2  708.15
   330.7  708.22   334.6  709.26   337.6  710.41   341.1  711.07   365.5  710.77
   403.8  712.08   438.4  712.11   507.6  714.69   520.8  714.63   560.3  713.43
   573.5  713.45   609.8  714.11   632.9  714.04   642.7  714.64   656.2  715.02
#Mann= 4 ,-1,0
       0     .05       0  297.52      .1       0     316    .045       0
   334.6      .1       0
Bank Sta=316,334.6
XS Rating Curve= 0 ,0
Exp/Cntr(USF)=0,0
Exp/Cntr=0.3,0.1

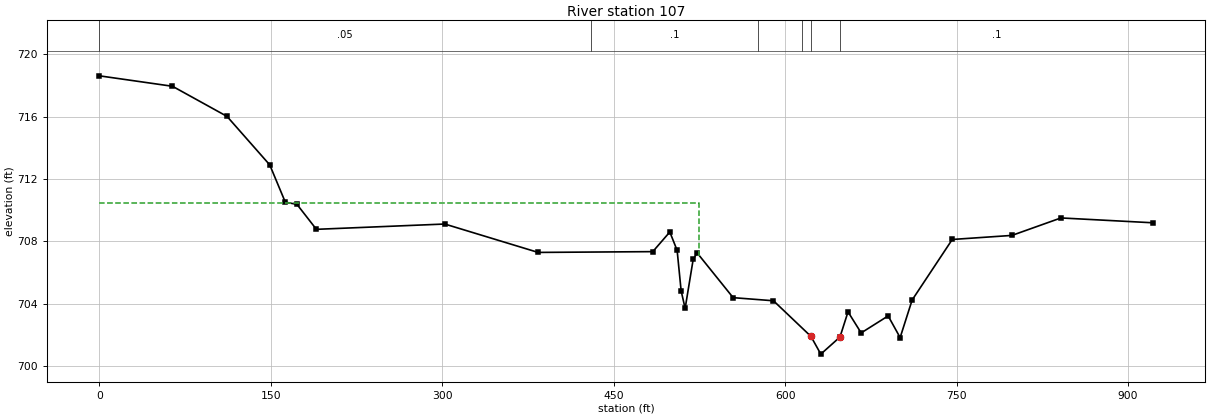
Type RM Length L Ch R = 1 ,107     ,,,
XS GIS Cut Line= 6
1644855.55066186 553269.712175971645315.02987673553143.278831401
1645362.99303096553024.3078870281645371.04279596552981.944518383
1645337.23547302552893.1473681141645347.01654543552714.833575929
#Sta/Elev= 30
       0  718.62      64  717.95   111.7  716.02   149.1  712.91   162.7  710.52
   172.9  710.38   189.9  708.78   302.2  709.12   383.9   707.3   484.2  707.35
   499.1  708.61   505.5  707.43     509  704.84   512.5  703.71   519.6  706.88
   523.1  707.26   554.5   704.4   589.8   704.2622.5584701.9169   631.2  700.78
647.9584701.8759     655  703.49   666.5  702.14   690.1  703.23   700.6  701.84
   711.1  704.25   746.2  708.13   798.4  708.39   841.3  709.51   921.6   709.2
#Mann= 6 ,-1,0
       0     .05       0     430      .1       0  576.56     .08       0
  614.83      .1       0622.5584    .045       0647.9584      .1       0
#XS Ineff= 2 , 0
          524.91  710.48
Permanent Ineff=
       F       F
Bank Sta=622.5584,647.9584
XS Rating Curve= 0 ,0
Exp/Cntr(USF)=0,0
Exp/Cntr=0.3,0.1
LCMann Table=0

Chan Stop Cuts=-1
Use User Specified Reach Order=0
Composite Channel Slope=5